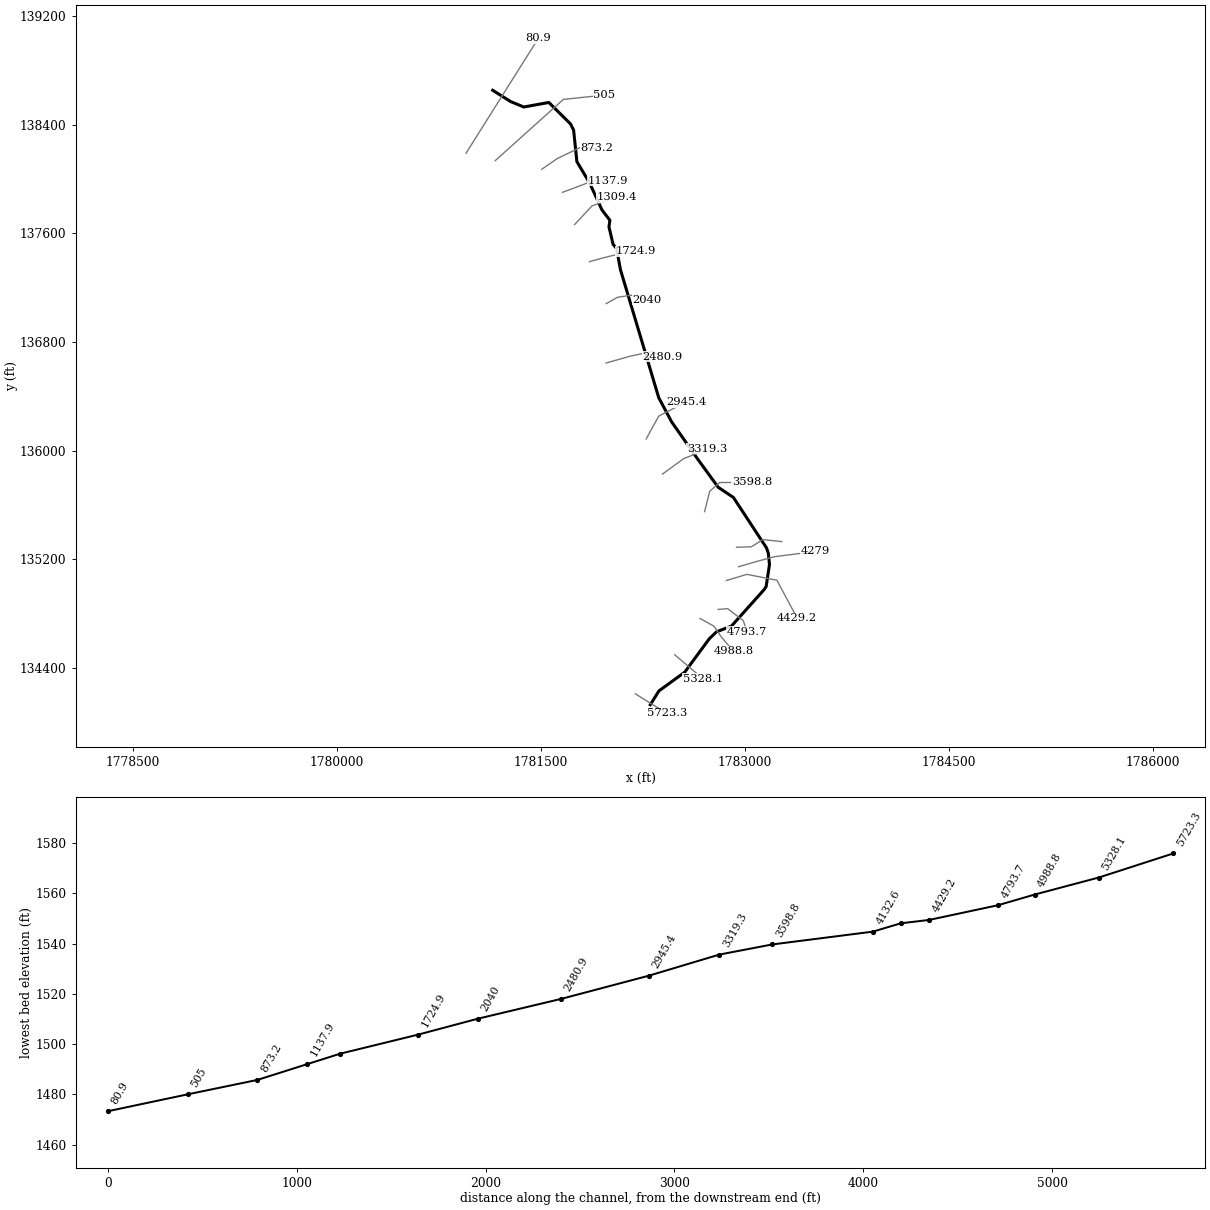
--- Clear Fork B.prj (project) ---

Proj Title=Clear Fork B
Current Plan=p01
Default Exp/Contr=0,0
English Units
Geom File=g01
Flow File=f01
Plan File=p01
BEGIN DESCRIPTION:
END DESCRIPTION:
DSS Export Rating Curves= 0
DSS Export Rating Curve Sorted= 0
DSS Export Volume Flow Curves= 0
DXF OffsetX= 0
DXF OffsetY= 0
DXF ScaleX= 0
DXF ScaleY= 0

--- Clear Fork B.p01 (plan) ---

Plan Title=Floodplain
Program Version=4.00
Geom File=g01
Flow File=f01
K Sum by GR=0
Std Step Tol=0.01
Critical Tol=0.01
Num of Std Step Trials=20
Max Error Tol=0.3
Flow Tol Ratio=0.001
Split Flow NTrial=30
Split Flow Tol=0.02
Split Flow Ratio=0.02
Log Output Level=0
Friction Slope Method=1
Unsteady Friction Slope Method=2
Unsteady Bridges Friction Slope Method=1
Global Log Level=0
CheckData=False
Run HTab=0
Run UNet=0
Run PostProcess=0
UNET Theta=0
UNET Theta Warmup=0
UNET ZTol=0
UNET ZSATol=0
UNET MxIter=0
UNET MaxInSteps=0
UNET DtIC=0
UNET DtMin=0
UNET MaxCRTS=0
UNET WFStab=0
UNET SFStab=0
UNET WFX=0
UNET SFX=0
UNET DSS MLevel=0
UNET DZMax Abort=0
UNET Convert EG Bridges=0
UNET Use Existing IB Tables=0
UNET Froude Limit=0
UNET Froude Power=0
Write IC File=0
Echo Input=False
Echo Output=False
Write Detailed=0

--- Clear Fork B.f01 (steady flow) ---

Flow Title=NFF Regression Equation
Program Version=4.00
Number of Profiles=1
Profile Names=P100yr
River Rch & RM=Clear Fork B,Main      ,5723.3
558.5007
River Rch & RM=Clear Fork B,Main      ,4429.2
583.9427
River Rch & RM=Clear Fork B,Main      ,4132.6
973.2358
River Rch & RM=Clear Fork B,Main      ,2040
1011.087
River Rch & RM=Clear Fork B,Main      ,1137.9
1123.295
Boundary for River Rch & Prof#=Clear Fork B,Main      ,1
Up Type=0
Dn Type=3
Dn Slope=0.01595

--- Clear Fork B.g01 (geometry) ---

Geom Title=Geometry
Program Version=4.00

River Reach=Clear Fork B    ,Main
Reach XY= 30
     1782305.082      134127.418     1782368.694      134229.391
     1782557.719      134366.753     1782738.833      134613.459
     1782791.631      134664.748     1782901.807      134706.836
     1783143.477      134977.322      1783157.23       134999.59
     1783181.463      135160.048     1783172.726      135245.649
     1783158.944      135284.154     1782915.853      135655.161
     1782804.223      135729.837      1782647.04      135946.619
     1782462.349      136211.211     1782367.384      136389.352
     1782085.764      137332.452     1782057.253      137488.277
     1782031.342      137520.354     1782001.172      137648.577
     1782007.941      137697.206     1781949.539      137773.875
     1781858.503      137972.974     1781765.222      138129.302
     1781741.053      138362.122     1781718.451      138407.172
     1781558.883      138565.516      1781374.78      138532.107
     1781278.696      138571.783     1781145.923      138655.455

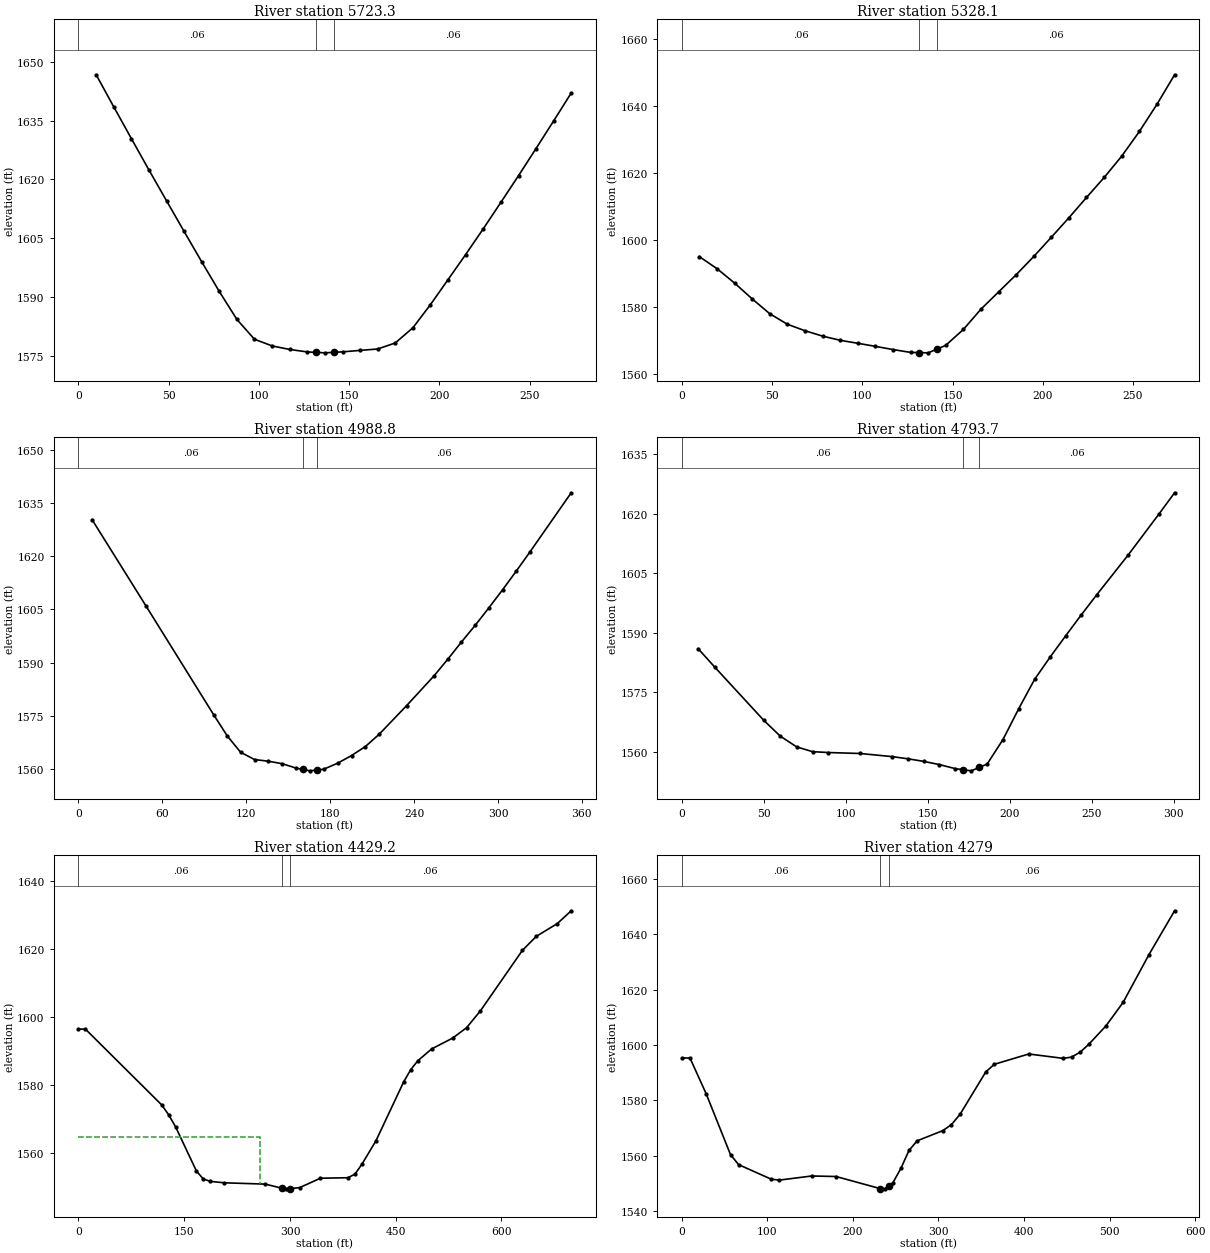
Type RM Length L Ch R = 1 ,5723.3  ,398.2,395.2,392.3
XS GIS Cut Line= 3
     1782194.561      134208.148     1782310.375      134135.902
     1782426.188      134063.656
#Sta/Elev= 30
     9.8 1646.65    19.5 1638.52    29.3 1630.41      39 1622.44    48.8 1614.56
    58.5 1606.78    68.2  1599.1      78 1591.49    87.8 1584.35    97.5 1579.32
   107.3 1577.62     117 1576.72   126.8 1576.09   131.5 1575.98   136.5 1575.86
   141.5 1575.99   146.3 1576.11     156 1576.48   165.8 1576.84   175.5 1578.37
   185.3 1582.25     195 1588.13   204.7 1594.46   214.5 1600.88   224.3 1607.46
     234 1614.15   243.8 1620.96   253.5 1627.87   263.3 1634.93     273    1642
#Mann= 3 , 0 , 0
       0     .06       0   131.5    .045       0   141.5     .06       0
Bank Sta=131.5,141.5
XS Rating Curve= 0 ,0
Exp/Cntr=0.3,0.1

Type RM Length L Ch R = 1 ,5328.1  ,344.7,339.3,333.9
XS GIS Cut Line= 3
     1782484.433      134495.901     1782588.399      134407.452
     1782692.365      134319.003
#Sta/Elev= 30
     9.7 1595.01    19.5  1591.4    29.2 1587.11      39 1582.37    48.7 1577.96
    58.5  1574.8    68.3 1572.86      78 1571.26    87.7 1570.02    97.5 1569.12
   107.2 1568.21     117 1567.25   126.7  1566.4   131.5 1566.33   136.5 1566.27
   141.5 1567.42   146.2 1568.51     156 1573.26   165.7  1579.3   175.5 1584.47
   185.2 1589.58     195 1595.05   204.7 1600.78   214.5 1606.64   224.2 1612.67
     234 1618.65   243.7 1625.01   253.5 1632.38   263.3 1640.55     273 1649.32
#Mann= 3 , 0 , 0
       0     .06       0   131.5    .045       0   141.5     .06       0
Bank Sta=131.5,141.5
XS Rating Curve= 0 ,0
Exp/Cntr=0.3,0.1

Type RM Length L Ch R = 1 ,4988.8  ,192.2,195.1,201.2
XS GIS Cut Line= 4
      1782670.95      134762.801     1782772.497      134706.843
      1782828.66      134625.151     1782917.492      134520.395
#Sta/Elev= 27
     9.7 1630.26    48.3 1605.93    96.6 1575.35   106.3 1569.39   115.9 1564.75
   125.9 1562.68   135.8 1562.21   145.7 1561.51   155.6 1560.28   160.5 1559.89
   165.5  1559.5   170.5 1559.73   175.4 1559.96   185.3 1561.64   195.3 1563.81
   205.2 1566.35   215.1 1569.82   234.7 1577.88   254.3 1586.26   264.1 1590.93
   273.9 1595.78   283.8 1600.52   293.6 1605.46   303.4 1610.54   313.2 1615.81
     323 1621.22   352.4 1637.82
#Mann= 3 , 0 , 0
       0     .06       0   160.5    .045       0   170.5     .06       0
Bank Sta=160.5,170.5
XS Rating Curve= 0 ,0
Exp/Cntr=0.3,0.1

Type RM Length L Ch R = 1 ,4793.7  ,354.9,364.5,374
XS GIS Cut Line= 4
     1782804.264      134829.741     1782874.033      134835.398
     1782989.057      134746.773     1783015.456      134665.691
#Sta/Elev= 27
      10 1585.99      20  1581.4      50 1567.95      60 1563.99      70 1561.28
    79.7 1560.07    89.4 1559.85   108.7 1559.61   128.1 1558.83   137.8 1558.28
   147.4 1557.63   157.1 1556.81   166.8 1555.79   171.5 1555.52   176.5 1555.24
   181.5 1556.12   186.2 1556.95   195.8 1563.09   205.5 1570.93   215.2 1578.33
   224.7 1583.95   234.2 1589.32   243.6 1594.53   253.1 1599.63   272.1 1609.56
     291 1619.95   300.5 1625.29
#Mann= 3 , 0 , 0
       0     .06       0   171.5    .045       0   181.5     .06       0
Bank Sta=171.5,181.5
XS Rating Curve= 0 ,0
Exp/Cntr=0.3,0.1

Type RM Length L Ch R = 1 ,4429.2  ,141.1,150.2,159.3
XS GIS Cut Line= 4
     1782864.605      135042.818     1783015.456      135088.073
     1783236.075      135044.703     1783385.062       134765.29
#Sta/Elev= 30
       0 1596.42     9.8 1596.42   118.1 1574.09     128 1571.17   137.8 1567.62
   167.3 1554.65     177  1552.3   186.8  1551.6   206.4 1551.17     265 1550.78
   289.4 1549.53   294.4 1549.39   299.4 1549.42   313.9 1549.76   343.2 1552.52
   382.3 1552.66   392.2 1553.72   402.1 1556.64   421.9  1563.5   461.5 1580.96
   471.4 1584.49   481.3 1587.09   501.1  1590.6   530.8 1593.77   550.6 1596.84
   570.3 1601.83   629.7 1619.59   649.5 1623.73   679.2 1627.48     699 1631.26
#Mann= 3 , 0 , 0
       0     .06       0   289.4    .045       0   299.4     .06       0
#XS Ineff= 2 , 0
          257.72  1564.8
Permanent Ineff=
       F       F
Bank Sta=289.4,299.4
XS Rating Curve= 0 ,0
Exp/Cntr=0.3,0.1

Type RM Length L Ch R = 1 ,4279    ,140.3,146.4,151.8
XS GIS Cut Line= 4
     1782954.215      135144.361     1783090.881       135184.24
     1783219.104      135218.182     1783517.649      135256.832
#Sta/Elev= 30
       0  1595.3     9.5  1595.3    28.5 1582.33    56.9 1560.38    66.4 1556.78
   104.4 1551.55   113.9  1551.2   151.8 1552.69   180.3  1552.5   232.1 1548.11
   237.1 1548.05   242.1 1549.18   246.6 1550.19   256.1 1555.45   265.5  1561.9
     275 1565.38   305.1 1569.08   315.1 1571.23   325.2 1574.95   355.3 1590.29
   365.3 1593.03   405.5 1596.75   445.6 1595.18   455.6 1595.62   465.7 1597.43
   475.7 1600.24   495.8  1606.9   515.8 1615.37   545.9 1632.54     576 1648.47
#Mann= 3 , 0 , 0
       0     .06       0   232.1    .045       0   242.1     .06       0
Bank Sta=232.1,242.1
XS Rating Curve= 0 ,0
Exp/Cntr=0.3,0.1

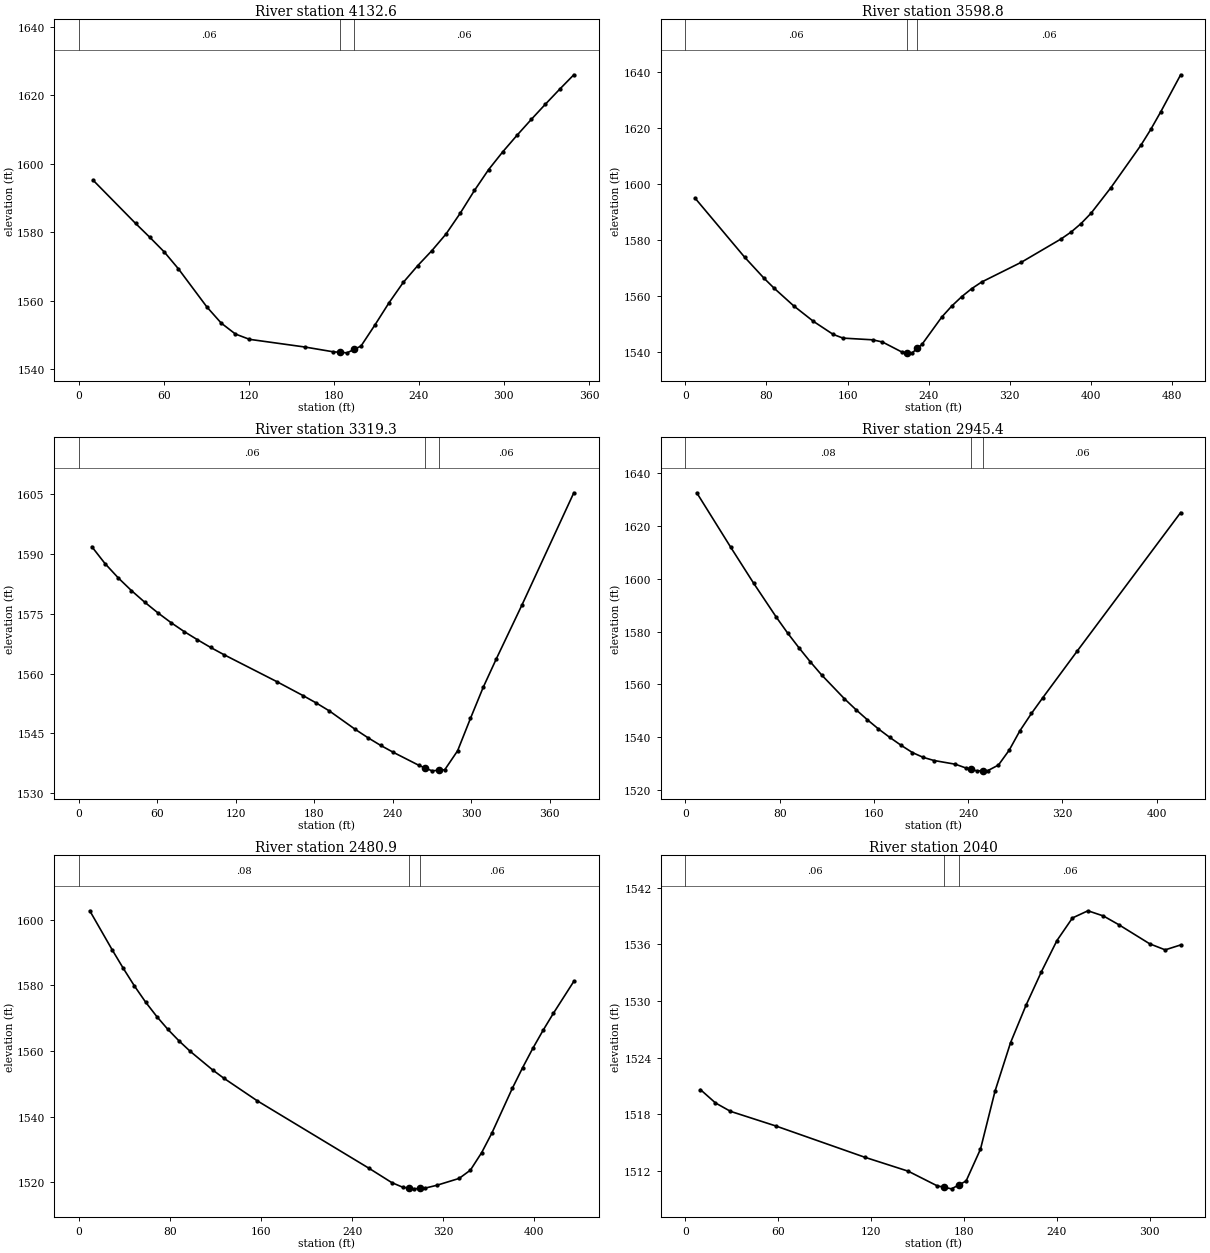
Type RM Length L Ch R = 1 ,4132.6  ,530.8,533.8,537.5
XS GIS Cut Line= 4
     1782938.823      135287.701     1783049.397      135291.722
     1783132.365      135344.519     1783271.902      135329.434
#Sta/Elev= 30
    10.1 1595.27    40.2 1582.58    50.3 1578.49    60.4 1574.25    70.4 1569.31
    90.5 1558.15   100.6 1553.44   110.6 1550.25   120.5  1548.7   159.8 1546.44
   179.5 1545.06   184.3 1544.91   189.3 1544.75   194.3 1545.75   199.2 1546.74
     209 1552.89     219 1559.42     229 1565.34   239.1  1570.2   249.1 1574.59
   259.1 1579.46   269.1 1585.52   279.2 1592.22   289.2 1598.32   299.2 1603.53
   309.2 1608.34   319.3 1612.99   329.3 1617.46   339.3 1621.81   349.3 1626.04
#Mann= 3 , 0 , 0
       0     .06       0   184.3    .045       0   194.3     .06       0
Bank Sta=184.3,194.3
XS Rating Curve= 0 ,0
Exp/Cntr=0.3,0.1

Type RM Length L Ch R = 1 ,3598.8  ,286.4,279.5,272.7
XS GIS Cut Line= 4
     1782704.326      135550.054     1782742.038      135700.905
     1782815.578      135765.016     1783051.283      135765.016
#Sta/Elev= 30
     9.7 1594.91    58.3 1573.92    77.7 1566.29    87.5 1562.78   106.9 1556.44
   126.3 1550.91   145.8 1546.24   155.5 1544.91   184.8  1544.3   194.5 1543.51
     214 1539.86   218.8 1539.75   223.8 1539.64   228.8  1541.2   233.5 1542.68
   253.1 1552.49   262.9  1556.4   272.7 1559.75   282.5  1562.6   292.3 1564.97
   331.6 1572.07   370.9 1580.43   380.7 1582.88   390.5 1585.91   400.4 1589.62
     420 1598.78   449.5  1613.9   459.3  1619.6   469.1 1625.86   488.8 1639.15
#Mann= 3 , 0 , 0
       0     .06       0   218.8    .045       0   228.8     .06       0
Bank Sta=218.8,228.8
XS Rating Curve= 0 ,0
Exp/Cntr=0.3,0.1

Type RM Length L Ch R = 1 ,3319.3  ,371.8,373.8,375.9
XS GIS Cut Line= 4
     1782395.081      135827.242     1782549.704       135940.38
      1782659.07       135983.75     1782721.296       136013.92
#Sta/Elev= 30
    10.1 1591.82    20.2 1587.57    30.3 1583.99    40.3 1580.83    50.4 1577.93
    60.5 1575.25    70.6 1572.78    80.7 1570.53    90.8 1568.49   100.8 1566.57
   110.9 1564.77   151.3 1558.01   171.4  1554.5   181.5 1552.65   191.6 1550.64
   211.2 1546.06     221 1543.94   230.8    1542   240.6 1540.24   260.2 1536.97
     265 1536.31     270 1535.62     275 1535.76   279.8  1535.9   289.6 1540.65
   299.4 1548.75   309.2 1556.59   319.1 1563.64   338.9 1577.29   378.4 1605.33
#Mann= 3 , 0 , 0
       0     .06       0     265    .045       0     275     .06       0
Bank Sta=265,275
XS Rating Curve= 0 ,0
Exp/Cntr=0.3,0.1

Type RM Length L Ch R = 1 ,2945.4  ,469.9,464.5,459.1
XS GIS Cut Line= 4
     1782274.401      136085.574     1782367.275      136254.463
     1782448.326      136296.204     1782569.678      136358.701
#Sta/Elev= 30
     9.6 1632.67    38.5 1611.96    57.8 1598.43    77.1 1585.51    86.7  1579.5
    96.4 1573.86     106 1568.56   115.6 1563.58   134.9 1554.58   144.6 1550.47
   154.2 1546.67   163.8 1543.12   173.5 1539.88   183.1 1536.89   192.7 1534.14
   201.9 1532.31     211 1531.13   229.2 1529.71   238.3 1528.26   242.4 1527.79
   247.4 1527.21   252.4 1527.24   256.6 1527.27   265.7  1529.4   274.8 1535.02
   283.9 1542.38   293.7 1548.96   303.4 1554.97   332.7 1572.71   420.4 1625.17
#Mann= 3 , 0 , 0
       0     .08       0   242.4    .045       0   252.4     .06       0
Bank Sta=242.4,252.4
XS Rating Curve= 0 ,0
Exp/Cntr=0.3,0.1

Type RM Length L Ch R = 1 ,2480.9  ,442.1,440.9,439.8
XS GIS Cut Line= 4
     1781980.242      136645.608     1782159.377       136696.52
     1782323.427      136730.461     1782395.081      136692.749
#Sta/Elev= 30
     9.8 1602.67    29.4 1590.82    39.2 1585.15      49 1579.77    58.8 1574.86
    68.6 1570.47    78.4 1566.53    88.2 1563.02      98 1559.85   117.6 1554.21
   127.4 1551.69   156.8  1544.8   255.2 1524.18   274.9 1519.88   284.8 1518.43
   289.6 1518.21   294.6 1517.98   299.6 1518.11   304.5 1518.23   314.3 1519.05
     334 1521.15   343.9 1523.67   353.8 1529.01   362.8 1534.99   380.7 1548.58
   389.7 1554.85   398.7 1560.76   407.7 1566.25   416.7 1571.41   434.7 1581.17
#Mann= 3 , 0 , 0
       0     .08       0   289.6    .045       0   299.6     .06       0
Bank Sta=289.6,299.6
XS Rating Curve= 0 ,0
Exp/Cntr=0.3,0.1

Type RM Length L Ch R = 1 ,2040    ,313.3,315.1,316.9
XS GIS Cut Line= 4
     1781980.242      137083.075     1782065.095      137130.216
      1782166.92      137145.301     1782281.943       137111.36
#Sta/Elev= 24
     9.7 1520.61    19.4  1519.2    29.1 1518.31    58.2 1516.77   115.8 1513.45
   143.9 1511.97   162.6 1510.42   166.9 1510.27   171.9  1510.1   176.9 1510.54
   181.3 1510.93   190.6 1514.31     200 1520.46     210 1525.58     220 1529.55
     230 1533.12     240 1536.41     250  1538.8     260 1539.56     270 1539.01
     280 1538.08   299.9 1536.06   309.9 1535.42   319.9 1535.94
#Mann= 3 , 0 , 0
       0     .06       0   166.9    .045       0   176.9     .06       0
Bank Sta=166.9,176.9
XS Rating Curve= 0 ,0
Exp/Cntr=0.3,0.1

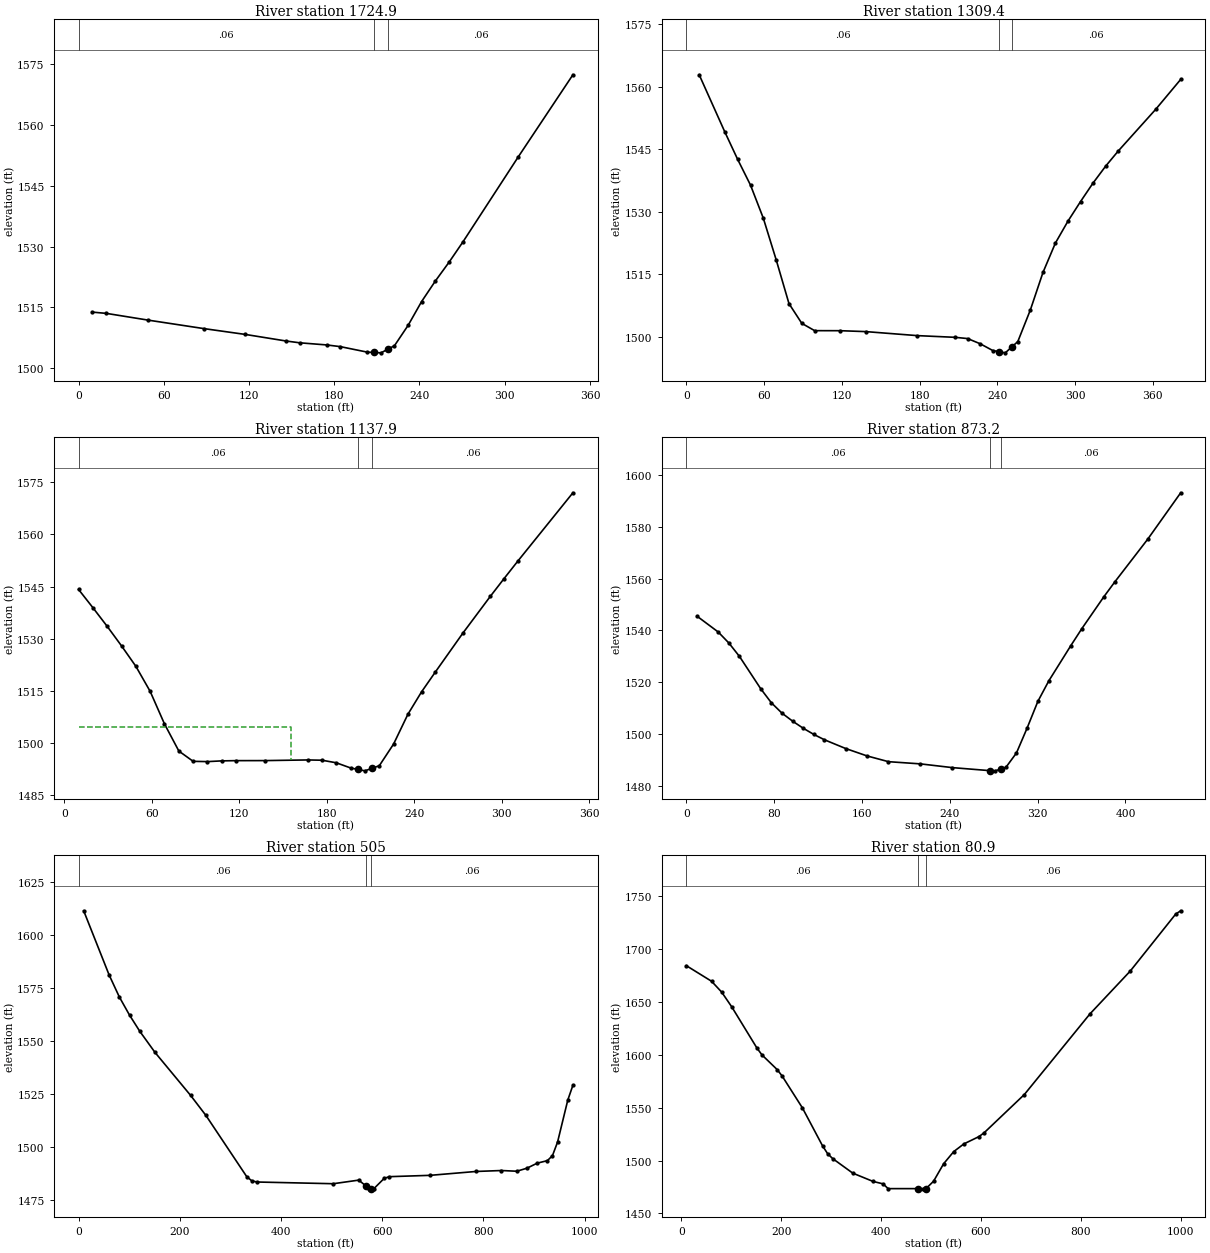
Type RM Length L Ch R = 1 ,1724.9  ,413.3,415.5,417.8
XS GIS Cut Line= 4
     1781857.675      137392.319      1781961.63      137421.312
     1782091.494       137452.66     1782196.552      137470.157
#Sta/Elev= 21
     9.8 1513.84    19.6 1513.53    49.1 1511.86    88.3 1509.77   117.5 1508.33
   146.1 1506.71   155.6 1506.27   174.7 1505.74   184.3 1505.32   203.3 1503.96
   207.9 1503.88   212.9 1503.79   217.9 1504.72   222.4 1505.56     232 1510.58
   241.5 1516.46   251.2 1521.54   260.9 1526.21   270.6 1531.19   309.3 1552.05
     348 1572.44
#Mann= 3 , 0 , 0
       0     .06       0   207.9    .045       0   217.9     .06       0
Bank Sta=207.9,217.9
XS Rating Curve= 0 ,0
Exp/Cntr=0.3,0.1

Type RM Length L Ch R = 1 ,1309.4  ,171.2,171.5,171.8
XS GIS Cut Line= 3
     1781748.308      137665.737     1781876.532      137803.388
     1782058.594      137868.643
#Sta/Elev= 30
     9.9 1562.84    29.7 1549.12    39.6 1542.54    49.5 1536.38    59.4 1528.43
    69.3 1518.48    79.2 1507.95    89.1 1503.22      99 1501.47   118.8 1501.46
   138.6 1501.24   178.2 1500.28   207.5 1499.87   217.1 1499.57   226.8 1498.32
   236.5  1496.7   241.1 1496.43   246.1 1496.15   251.1 1497.54   255.8 1498.86
   265.5 1506.46   275.2 1515.42   284.8 1522.48   294.5 1527.74   304.2 1532.43
   313.8 1536.85   323.5 1540.89   333.2 1544.52   362.2 1554.55   381.5 1561.73
#Mann= 3 , 0 , 0
       0     .06       0   241.1    .045       0   251.1     .06       0
Bank Sta=241.1,251.1
XS Rating Curve= 0 ,0
Exp/Cntr=0.3,0.1

Type RM Length L Ch R = 1 ,1137.9  ,262.8,264.7,266.6
XS GIS Cut Line= 3
     1781659.684      137903.327     1781880.303      137986.295
     1781993.441       137988.18
#Sta/Elev= 30
     9.8 1544.15    19.6 1538.93    29.5 1533.52    39.3 1527.93    49.1 1522.08
    58.9 1514.89    68.7 1505.56    78.6 1497.74    88.4 1494.79    98.2 1494.71
     108 1494.92   117.9 1494.99   137.5    1495     167 1495.19   176.8 1495.11
   186.6 1494.37   196.4 1492.89   201.2 1492.48   206.2 1492.06   211.2  1492.8
   216.1 1493.53   225.9 1499.76   235.7  1508.3   245.1 1514.76   254.6 1520.48
   273.4  1531.6   292.3  1542.2   301.7 1547.29   311.1 1552.29   348.9 1571.92
#Mann= 3 , 0 , 0
     9.8     .06       0   201.2    .045       0   211.2     .06       0
#XS Ineff= 2 , 0
          155.62 1504.72
Permanent Ineff=
       F       F
Bank Sta=201.2,211.2
XS Rating Curve= 0 ,0
Exp/Cntr=0.3,0.1

Type RM Length L Ch R = 1 ,873.2   ,362.5,368.1,373.8
XS GIS Cut Line= 4
     1781506.947      138073.034       1781618.2      138150.345
     1781784.136      138231.427     1781914.244      138229.542
#Sta/Elev= 30
     9.7 1545.52      29 1539.41    38.7 1535.16    48.4 1529.95    67.7  1517.5
    77.4 1512.07    87.1 1508.05    96.8 1504.95   106.4 1502.23   116.1 1499.83
   125.8 1497.76   145.2 1494.37   164.6 1491.52   184.1  1489.3   213.2 1488.45
   242.4    1487   276.3 1485.84   281.3 1485.76   286.3 1486.43     291 1487.07
   300.7 1492.67   310.4 1502.29   320.2 1512.61   330.2 1520.56   350.2 1534.13
   360.2 1540.68   380.2 1552.96   390.2 1558.72   420.3 1575.29   450.3  1593.2
#Mann= 3 , 0 , 0
       0     .06       0   276.3    .045       0   286.3     .06       0
Bank Sta=276.3,286.3
XS Rating Curve= 0 ,0
Exp/Cntr=0.3,0.1

Type RM Length L Ch R = 1 ,505     ,413.7,424.2,432.1
XS GIS Cut Line= 3
     1781164.594        138136.7     1781665.788        138588.1
     1781966.616      138619.592
#Sta/Elev= 30
    10.1 1611.47    60.4 1581.12    80.5 1570.76   100.7 1562.16   120.8 1554.57
     151 1544.54   221.5 1524.18   251.7 1514.73   332.2 1485.85   342.3 1483.83
   352.4 1483.27   503.4 1482.46   553.7 1484.16   568.8 1481.24   573.8 1480.04
   578.8 1480.11   583.9 1480.19     604 1484.98   614.1 1485.79   694.7 1486.42
   785.4 1488.25   835.8  1488.7   866.1 1488.36   886.2  1489.8   906.4 1492.17
   926.6 1493.37   936.6 1495.73   946.7 1502.16   966.9 1522.01     977 1528.99
#Mann= 3 , 0 , 0
       0     .06       0   568.8    .045       0   578.8     .06       0
Bank Sta=568.8,578.8
XS Rating Curve= 0 ,0
Exp/Cntr=0.3,0.1

Type RM Length L Ch R = 1 ,80.9    ,81.5,80.9,80.3
XS GIS Cut Line= 2
     1780949.852      138191.232     1781481.677      139038.104
#Sta/Elev= 30
    10.1  1684.3    60.6 1669.56    80.8 1659.31     101 1645.36   151.5 1606.35
   161.6 1599.88   191.9 1586.08     202 1579.89   242.4  1549.9   282.8 1513.96
   292.9 1506.59     303 1501.92   343.4 1488.12   383.8 1480.33     404    1478
   414.1  1473.5   474.8  1473.5   484.9  1473.3   489.9  1473.5   505.1 1480.48
   525.3 1497.04   545.5 1508.51   565.7 1515.76     596 1522.69   606.1 1526.19
   686.9 1562.47   818.2 1638.66     899 1679.22   989.9 1733.05    1000 1736.21
#Mann= 3 , 0 , 0
    10.1     .06       0   474.8    .045       0   489.9     .06       0
Bank Sta=474.8,489.9
XS Rating Curve= 0 ,0
Exp/Cntr=0.3,0.1
Stream Node=Clear Fork B    ,Main            , 0 , 0 ,Upstream end
Stream Node=Clear Fork B    ,Main            , 0 , 1 ,Downstream end

Chan Stop Cuts=-1
Use User Specified Reach Order=0